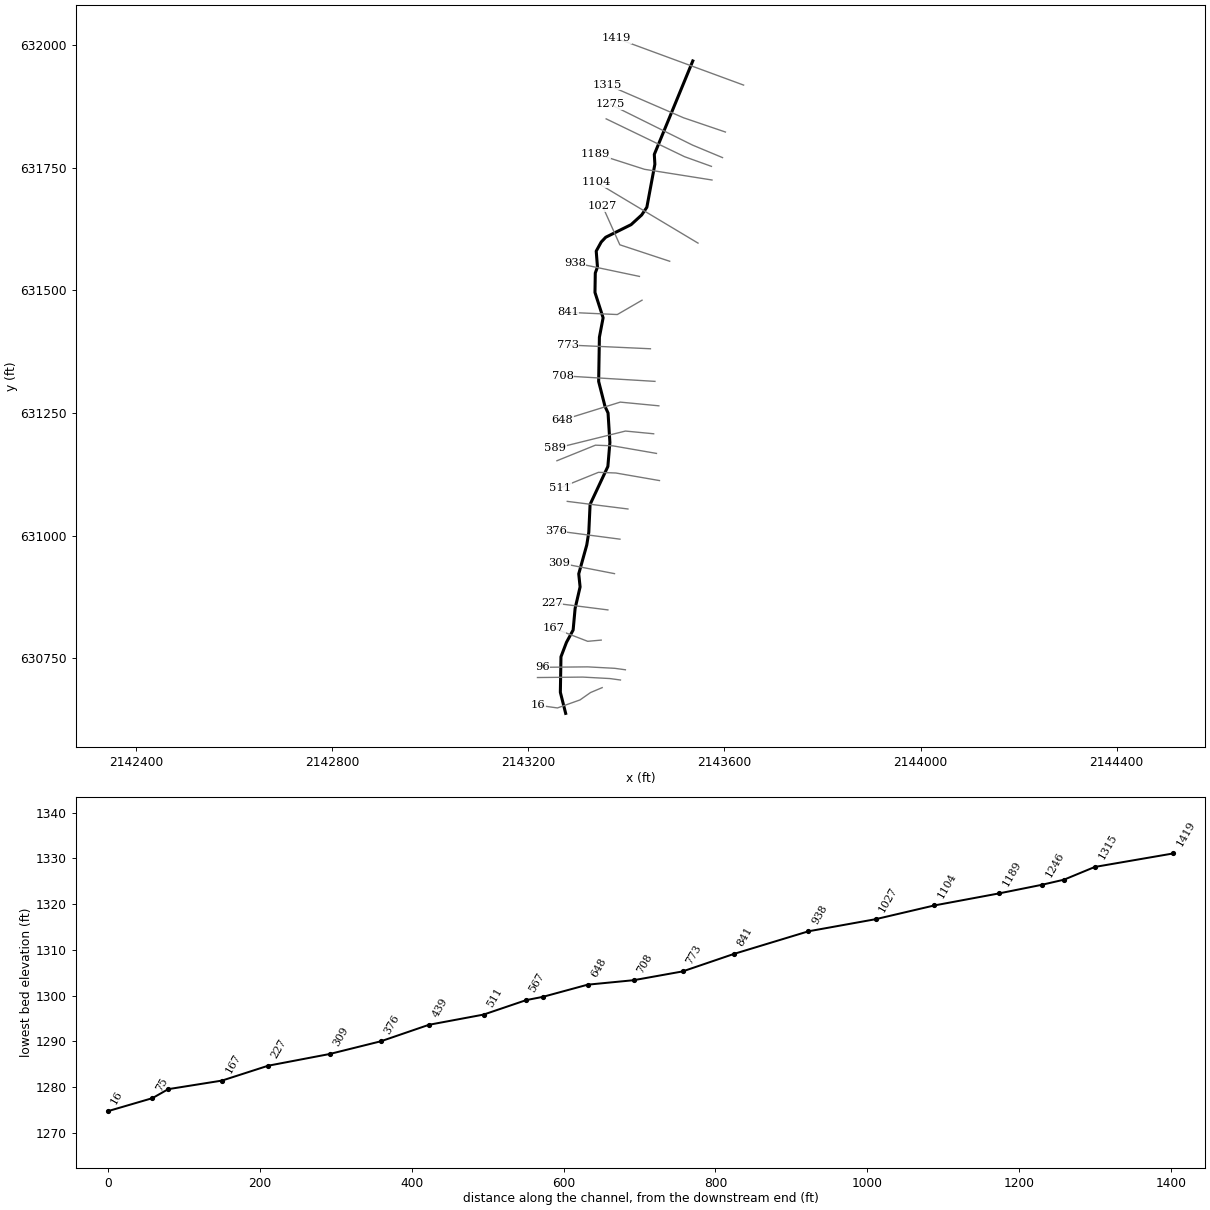
--- HONEYCMPRN.prj (project) ---

Proj Title=HONEYCMPRN
Current Plan=p01
Default Exp/Contr=0,0
English Units
Geom File=g01
Flow File=f01
Plan File=p01
BEGIN DESCRIPTION:
---------- MODELED AS PART OF WVEMD CTP PROGRAM, 2023----------
Stream Name: Honey Camp Run
Flood Zone:  AFH
Upshur County, WV
HEC-RAS Version: RAS 6.3
Vertical Datum: NAVD88
Projection: NAD 1983 StatePlane West Virginia S FIPS 4702 (US Feet)
Terrain: 1-meter LIDAR (FEMA Region III 3DEP collected 2016-2018)
Land Use: 2019 NLCD
Hydrologic Method:
WV SIR2010-5033 regression equations
Additional Model Notes:
None
END DESCRIPTION:
DSS Export Rating Curves= 0
DSS Export Rating Curve Sorted= 0
DSS Export Volume Flow Curves= 0
DXF OffsetX= 0
DXF OffsetY= 0
DXF ScaleX= 0
DXF ScaleY= 0

--- HONEYCMPRN.p01 (plan) ---

Plan Title=Floodplain
Program Version=6.30
Short Identifier=Floodplain
Geom File=g01
Flow File=f01
Subcritical Flow
K Sum by GR= 0
Std Step Tol= 0.01
Critical Tol= 0.01
Num of Std Step Trials= 20
Max Error Tol= 0.3
Flow Tol Ratio= 0.001
Split Flow NTrial= 30
Split Flow Tol= 0.02
Split Flow Ratio= 0.02
Log Output Level= 0
Friction Slope Method= 1
Unsteady Friction Slope Method= 2
Unsteady Bridges Friction Slope Method= 1
Parabolic Critical Depth
Global Vel Dist= 0 , 0 , 0
Global Log Level= 0
CheckData=False
Encroach Param=-1 ,0,0, 0
Mapping Interval=1HOUR
Computation Time Step Use Courant=        0
Computation Time Step Use Time Series=    0
Computation Time Step Count To Double=0
Computation Time Step Max Doubling=0
Computation Time Step Max Halving=0
Computation Time Step Residence Courant=0
Run HTab= 0
Run UNet= 0
Run Sediment= 0
Run PostProcess= 0
Run WQNet= 0
Run RASMapper=-1
UNET Theta= 0
UNET Theta Warmup= 0
UNET ZTol= 0
UNET ZSATol= 0
UNET MxIter= 0
UNET Max Iter WO Improvement= 0
UNET MaxInSteps= 0
UNET DtIC= 0
UNET DtMin= 0
UNET MaxCRTS= 0
UNET WFStab= 0
UNET SFStab= 0
UNET WFX= 1
UNET SFX= 1
UNET Gravity=32.17405
UNET 1D Methodology=Finite Difference
UNET DSS MLevel= 1
UNET Pardiso=0
UNET DZMax Abort= 0
UNET Use Existing IB Tables= 0
UNET Froude Reduction=False
UNET Froude Limit= 0
UNET Froude Power= 0
UNET D1 Cores= 0
UNET WindReference=Eulerian
UNET WindDragFormulation=Hsu (1988)
UNET D2 Coriolis=0
UNET D2 Cores= 0
UNET D2 Theta= 1
UNET D2 Theta Warmup= 1
UNET D2 Z Tol= 0.01
UNET D2 Volume Tol= 0.01
UNET D2 Max Iterations= 20
UNET D2 Equation= 0
UNET D2 RampUpFraction=0.1
UNET D2 TimeSlices= 1
UNET D2 Turbulence Formulation=Non-Conservative (original)
UNET D2 Eddy Viscosity=0.3
UNET D2 Transverse Eddy Viscosity=0.1
UNET D2 Smagorinsky Mixing=0
UNET D2 BCVolumeCheck=0
UNET D2 Cores=0
UNET D2 SolverType=PARDISO (Direct)
UNET D2 Minimum Iterations= 3
UNET D2 Maximum Iterations= 30
UNET D2 Restart Number= 10
UNET D2 Relaxation Coeff=1.3
UNET D2 SOR Precondition Iterations= 10
UNET D2 ILUT Maximum Fill= 8
UNET D2 ILUT Tolerance=1E-08
UNET D2 Convergence Tolerance=0.00001
UNET D1D2 MaxIter= 0
UNET D1D2 ZTol=0.01
UNET D1D2 QTol=0.1
UNET D1D2 MinQTol=1
Write IC File= 0
Write IC File at Fixed DateTime=0
Write IC File at Sim End=0
Echo Input=False
Echo Parameters=False
Echo Output=False
Write Detailed= 0
HDF Write Warmup=0
HDF Write Time Slices=0
HDF Flush=0
HDF Compression= 1
HDF Chunk Size= 1
HDF Spatial Parts= 1
HDF Use Max Rows=0
HDF Fixed Rows= 1
Calibration Method= 0
Calibration Iterations= 20
Calibration Max Change=0.05
Calibration Tolerance=0.2
Calibration Maximum=1.5
Calibration Minimum=0.5
Calibration Optimization Method= 1
WQ AD Non Conservative
WQ ULTIMATE=-1
WQ Max Comp Step=1HOUR
WQ Output Interval=15MIN
WQ Output Selected Increments= 0
WQ Output face flow=0
WQ Output face velocity=0
WQ Output face area=0
WQ Output face dispersion=0
WQ Output cell volume=0
WQ Output cell surface area=0
WQ Output cell continuity=0
WQ Output cumulative cell continuity=0
WQ Output face conc=0
WQ Output face dconc_dx=0
WQ Output face courant=0
WQ Output face peclet=0
WQ Output face adv mass=0
WQ Output face disp mass=0
WQ Output cell mass=0
WQ Output cell source sink temp=0
WQ Output nsm pathways=0
WQ Output nsm derived pathways=0
WQ Create Restart=0
WQ Fixed Restart=0
WQ System Summary=0
WQ Write To DSS=0
Sorting and Armoring Iterations= 10
XS Update Threshold= 0.02
Bed Roughness Predictor= 0
Hydraulics Update Threshold= 0.02
Energy Slope Method= 1
Volume Change Method= 1
Sediment Retention Method= 0
Sediment TS Multiplier= 1
Warm Up Method= 0
XS Weighting Method= 0
Number of US Weighted Cross Sections= 1
Number of DS Weighted Cross Sections= 1
Upstream XS Weight=0
Main XS Weight=1
Downstream XS Weight=0
Number of DS XS's Weighted with US Boundary= 1
Upstream Boundary Weight= 1
Weight of XSs Associated with US Boundary= 0
Number of US XS's Weighted with DS Boundary= 1
Downstream Boundary Weight= 0.5
Weight of XSs Associated with DS Boundary= 0.5
Percentile Method= 0
Sediment Output Level= 3
Mass or Volume Output= 0
Output Increment Type= 1
Profile and TS Output Increment= 1
Transport Output Increment 1
XS Output Flag= 0
XS Output Increment= 10
Read HDF5 Sediment Hotstart= 0
Sediment Hotstart Type= 0
Write Gradation File= 0
Read Gradation Hotstart= 0
Write HDF5 File= 1
Write Binary Output= 1
Write DSS Sediment File= 0
DSS Sediment Output Type= 1
SV Curve= 0
Specific Gage Flag= 0
Subcell Erosion Methods= 0
Subcell Deposition Methods= 0
Advection Scheme= 1
Matrix Solver= 0
Implicit Weighting Factor= 1
Maximum Outer Loop Convergence Iterations= 5
Convergence Maximum Absolute= 0.001
Convergence RMSE= 0.0001
Grain Fractions Max Abs Error= 0.001
Max Subgrid Regions= 1
Max Subgrid Length Scale= 3.402823E+38
Initial Layer Thickness= 3.402823E+38
Min Layer Thickness= 3.402823E+38
Max Layer Thickness= 3.402823E+38
Number of Layers= 5

--- HONEYCMPRN.f01 (steady flow) ---

Flow Title=Flows
Program Version=6.30
Number of Profiles= 1
Profile Names=01pct
River Rch & RM=HONEYCMPRN,Main,1419
     578
Boundary for River Rch & Prof#=HONEYCMPRN,Main            , 1
Up Type= 0
Dn Type= 3
Dn Slope=0.05391
DSS Import GetInterval= 0
DSS Import GetPeak= 0
DSS Import FillOption= 0

--- HONEYCMPRN.g01 (geometry) ---

Geom Title=Geometry
Program Version=6.31

River Reach=HONEYCMPRN      ,Main
Reach XY= 30
2143535.34803239631968.182451956     2143456.815      631777.496
     2143457.959      631757.435     2143441.591      631669.612
     2143431.003       631653.93     2143409.483      631634.213
     2143357.688      631608.487     2143348.559      631598.843
     2143338.314      631580.214     2143340.861      631547.735
     2143336.426      631535.544     2143335.767       631495.91
     2143352.365      631444.229      2143344.81      631404.538
     2143343.265      631314.311     2143356.228      631263.488
     2143362.438       631250.01     2143366.215      631189.915
     2143362.066      631140.838     2143325.809      631063.431
     2143323.176       631006.77     2143319.027      630980.729
     2143302.658      630921.808     2143305.405      630895.138
     2143295.247      630851.154     2143291.212        630807.2
      2143277.59      630781.989     2143266.401        630752.6
     2143265.142      630680.171     2143275.988      630637.161

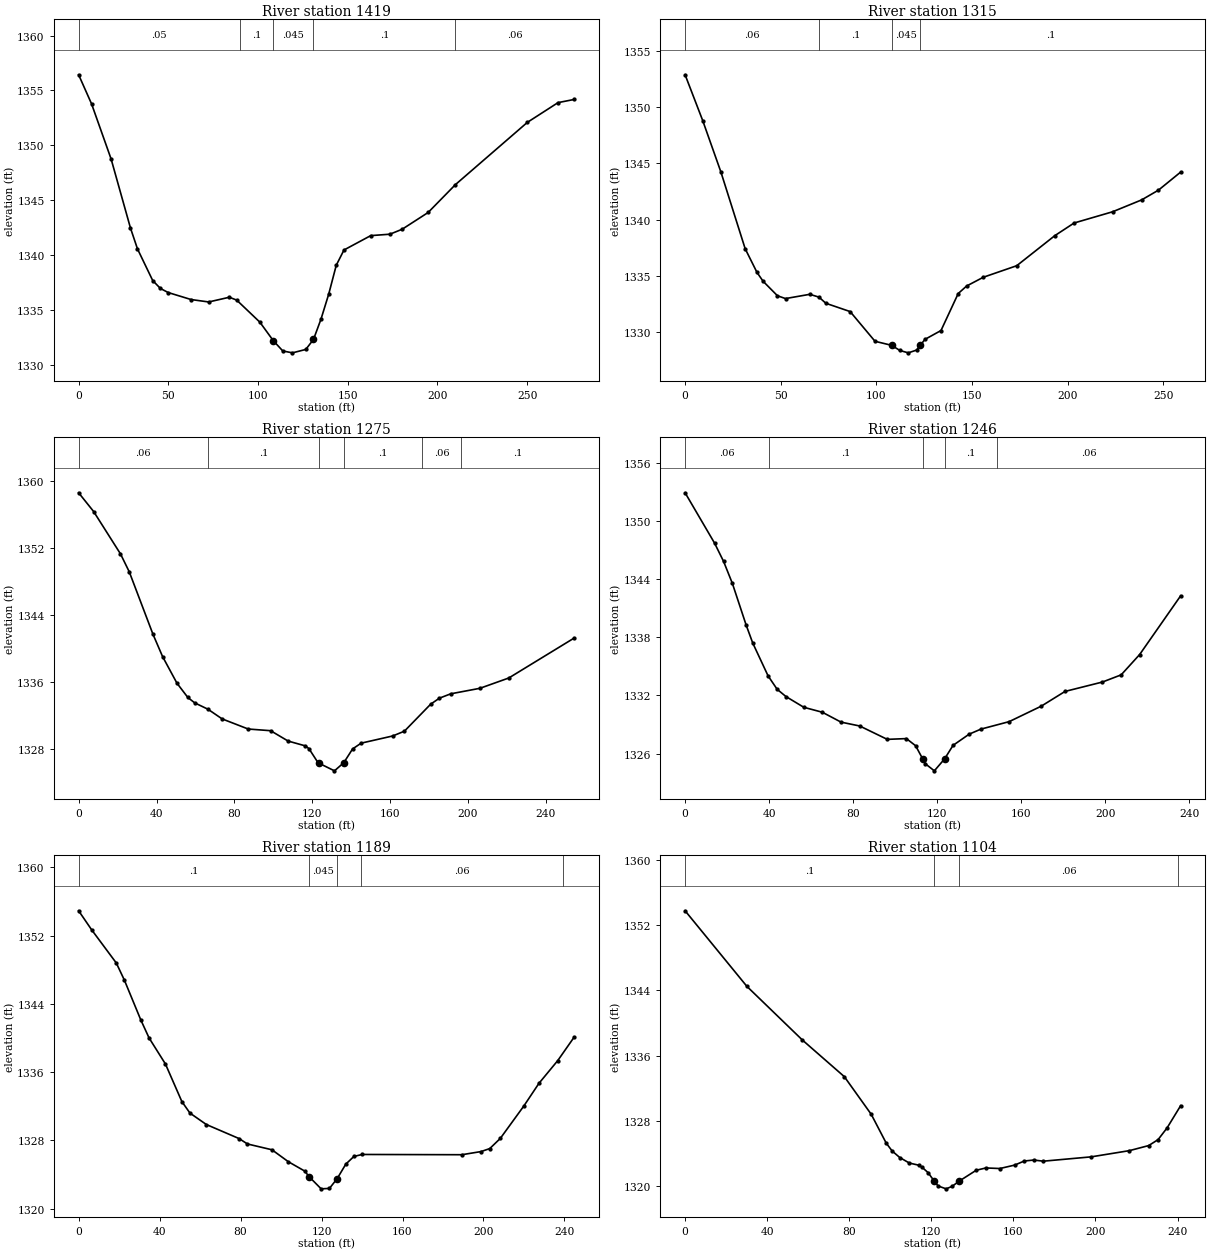
Type RM Length L Ch R = 1 ,1419    ,103.5,103.5,103.5
XS GIS Cut Line= 2
2143638.97521574631918.9201759082143379.78116169632014.299081921
#Sta/Elev= 30
       0 1356.43     7.2 1353.78    18.1 1348.75    28.9 1342.45    32.8 1340.55
    41.3 1337.66    45.6 1336.94    49.9 1336.57    62.7 1335.93    72.5 1335.71
      84 1336.14    88.1 1335.88     101 1333.87   108.5 1332.18   113.8 1331.24
   119.2 1331.07   126.6 1331.38   130.9 1332.29   135.1 1334.15   139.4 1336.43
   143.6 1339.06   147.9 1340.45   162.8 1341.76   173.5 1341.89   180.3 1342.34
   194.8 1343.87     210 1346.41   250.1 1352.09   267.2 1353.89   276.2 1354.18
#Mann= 5 ,-1,0
       0     .05       0      90      .1       0   108.5    .045       0
   130.9      .1       0     210     .06       0
Bank Sta=108.5,130.9
XS Rating Curve= 0 ,0
Exp/Cntr(USF)=0,0
Exp/Cntr=0.3,0.1

Type RM Length L Ch R = 1 ,1315    ,40.5,40.5,40.5
XS GIS Cut Line= 3
2143601.88489925631823.1774024442143516.44050636631852.232050159
2143361.44888294631919.338483851
#Sta/Elev= 30
       0 1352.91     9.2 1348.83    18.7 1344.25    31.4  1337.4    37.6 1335.28
    40.8 1334.49    48.3  1333.2    52.5 1332.95    65.2 1333.33      70 1333.08
    73.6 1332.53    86.3 1331.79    99.3 1329.14     108 1328.78   112.3 1328.32
   116.7 1328.11   121.1 1328.36  122.91 1328.77   125.4 1329.31   133.8  1330.1
   142.8  1333.4   147.2 1334.07   155.9 1334.85   173.4 1335.88   193.3 1338.56
   203.4 1339.69   223.5 1340.69   238.7 1341.75   247.5 1342.62   259.1 1344.23
#Mann= 4 ,-1,0
       0     .06       0      70      .1       0     108    .045       0
  122.91      .1       0
Bank Sta=108,122.91
XS Rating Curve= 0 ,0
Exp/Cntr(USF)=0,0
Exp/Cntr=0.3,0.1

Type RM Length L Ch R = 1 ,1275    ,29,29.1,29.2
XS GIS Cut Line= 3
2143595.98604827631770.9730408782143534.74974896631796.522232337
2143366.16823771 631880.12091703
#Sta/Elev= 30
       0 1358.58     7.7 1356.34    21.5 1351.27      26 1349.13    38.2 1341.65
    43.1    1339    50.5 1335.81    56.1  1334.1    59.6 1333.46    66.4  1332.7
    73.7 1331.54    87.1 1330.33    98.6 1330.13   107.6 1328.89   116.5 1328.31
   118.3 1327.98   122.8 1326.36123.65771326.217   131.4 1325.33   136.2 1326.31
   140.7 1327.95   145.1 1328.64   161.3  1329.5   167.3 1330.07   180.8  1333.3
   185.3 1334.02   191.1 1334.54   206.1  1335.2   220.9 1336.43   254.5 1341.21
#Mann= 6 ,-1,0
       0     .06       0   66.35      .1       0123.6577    .045       0
   136.2      .1       0  176.35     .06       0  196.35      .1       0
Bank Sta=123.6577,136.2
XS Rating Curve= 0 ,0
Exp/Cntr(USF)=0,0
Exp/Cntr=0.3,0.1

Type RM Length L Ch R = 1 ,1246    ,53.7,56.6,59.3
XS GIS Cut Line= 3
2143573.35528454631753.1126127092143518.60007148 631772.80239353
2143358.61732889631850.018039008
#Sta/Elev= 30
       0 1352.92      14 1347.73    18.3 1345.84    22.5 1343.56    29.1 1339.23
    32.2  1337.4    39.5 1334.01    43.8 1332.63      48 1331.88    56.5 1330.77
    65.3 1330.26    74.2 1329.24    83.1 1328.84    96.2 1327.46   105.3 1327.54
   109.7  1326.8112.98871325.471   114.2 1324.96   118.6 1324.21   123.5 1325.45
   127.5 1326.84   135.2    1328   140.8 1328.52   154.2 1329.29   169.5 1330.89
   180.8 1332.41   198.6 1333.38   207.5 1334.12   216.3 1336.22   235.8 1342.28
#Mann= 5 ,-1,0
       0     .06       0      40      .1       0112.9887    .045       0
   123.5      .1       0  148.19     .06       0
Bank Sta=112.9887,123.5
XS Rating Curve= 0 ,0
Exp/Cntr(USF)=0,0
Exp/Cntr=0.3,0.1

Type RM Length L Ch R = 1 ,1189    ,89.1,85.1,80.5
XS GIS Cut Line= 3
2143574.51358635631725.2882910992143436.88805353631747.090355705
2143336.50771441631779.339242934
#Sta/Elev= 30
       0 1354.92     6.4  1352.7    18.6  1348.8    22.6 1346.79    30.7 1342.13
    34.8 1340.01    42.9 1336.95      51 1332.55      55  1331.2    63.1 1329.86
    79.3 1328.21    83.4 1327.58    95.5  1326.9   103.6  1325.5   111.7  1324.4
     114 1323.71   119.8 1322.32   123.9 1322.37   127.7 1323.51     132 1325.22
     136 1326.12   140.1 1326.35   189.3 1326.32   198.8 1326.69   203.1 1327.04
   208.3 1328.23   219.9 1332.02   227.4 1334.69   236.7 1337.36   244.8 1340.11
#Mann= 5 ,-1,0
       0      .1       0     114    .045       0   127.7      .1       0
  139.34     .06       0  239.34      .1       0
Bank Sta=114,127.7
XS Rating Curve= 0 ,0
Exp/Cntr(USF)=0,0
Exp/Cntr=0.3,0.1

Type RM Length L Ch R = 1 ,1104    ,83.2,77.1,69.4
XS GIS Cut Line= 2
2143545.96508239631596.5512178682143338.72642554631720.608490922
#Sta/Elev= 30
       0 1353.77    30.1 1344.51    57.2 1337.92    77.6 1333.44    90.7 1328.83
      98  1325.3   100.9 1324.33   104.6 1323.53   109.3 1322.85     114 1322.58
   115.5 1322.33   118.4 1321.68   121.3 1320.68   123.3 1320.04   127.2 1319.69
   130.1 1319.99   133.6 1320.64   141.9 1321.97   146.6 1322.25   153.4 1322.18
   160.6  1322.6   165.3  1323.1   169.9 1323.22   174.6 1323.08   197.9 1323.61
   216.5 1324.37   225.9 1324.99   230.5 1325.72   234.9 1327.16   241.5 1329.88
#Mann= 4 ,-1,0
       0      .1       0   121.3    .045       0   133.6     .06       0
     240      .1       0
Bank Sta=121.3,133.6
XS Rating Curve= 0 ,0
Exp/Cntr(USF)=0,0
Exp/Cntr=0.3,0.1

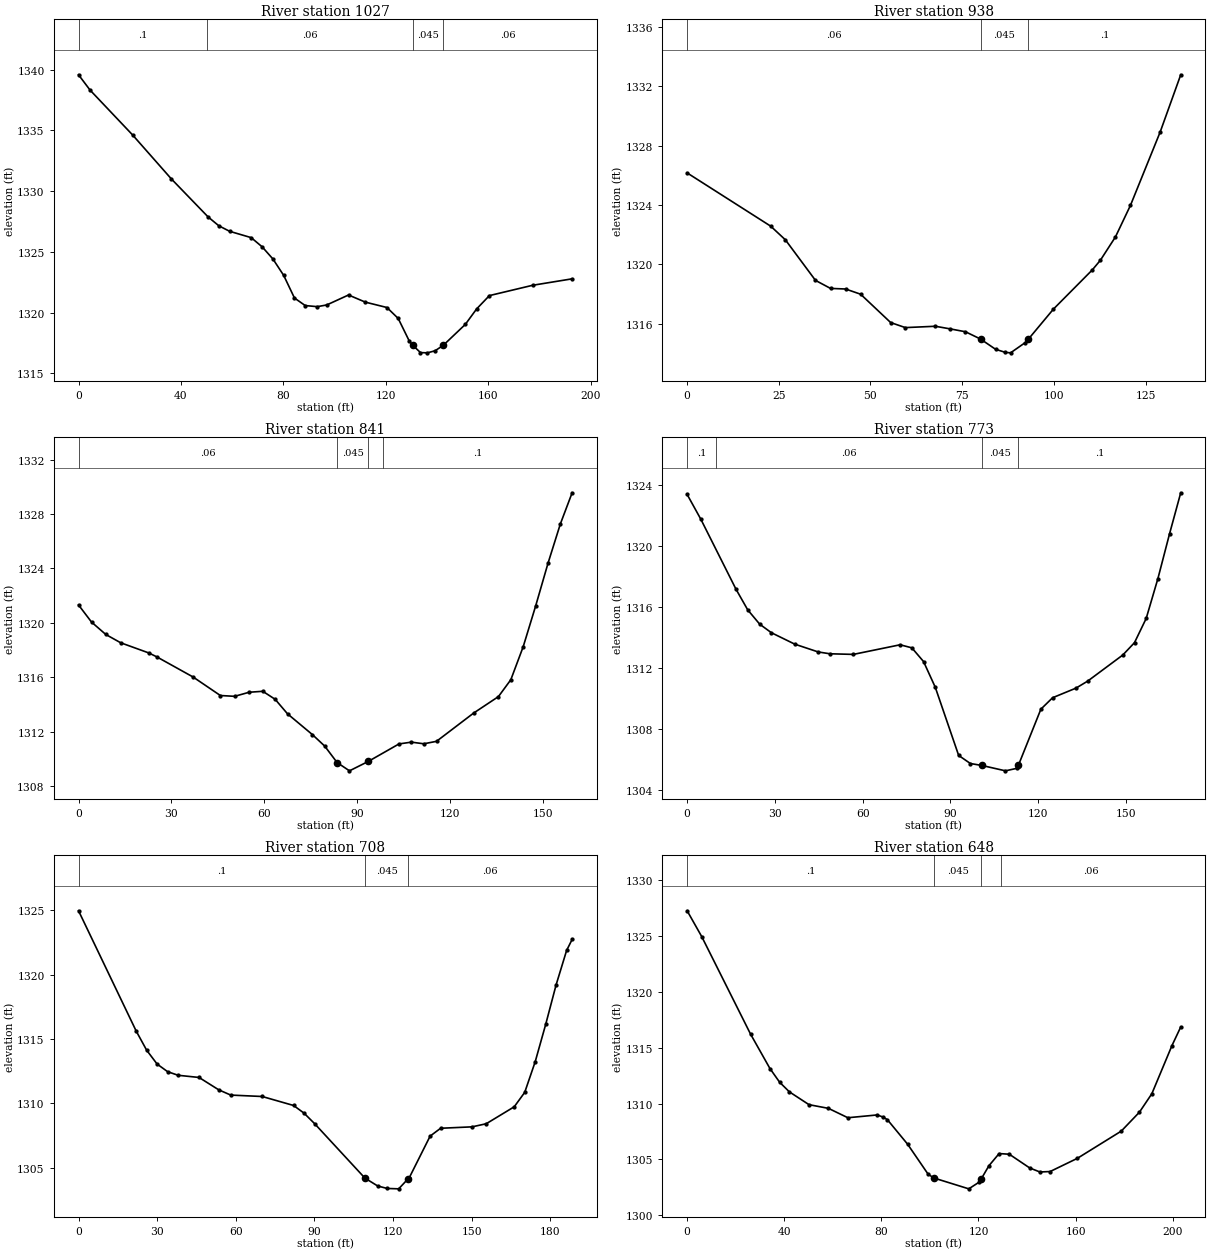
Type RM Length L Ch R = 1 ,1027    ,79.4,88.5,100.7
XS GIS Cut Line= 3
2143488.21374729631559.5017581622143386.47077913631593.113274429
2143351.49663383631671.237339265
#Sta/Elev= 30
       0 1339.57     4.5 1338.31    21.1 1334.62    36.2 1331.01    50.6 1327.87
    54.8 1327.14      59 1326.69    67.4 1326.17    71.7 1325.41    75.9 1324.41
    80.1 1323.06    84.3  1321.2    88.5 1320.58    93.2 1320.49    96.9 1320.63
   105.4 1321.45     112 1320.86   120.4 1320.42   124.8 1319.52   129.1 1317.67
   130.41317.327   133.5 1316.71   136.2 1316.69   139.2 1316.86   142.4 1317.31
     151 1319.03   155.4  1320.3   160.4  1321.4   177.3 1322.25   192.7 1322.78
#Mann= 4 ,-1,0
       0      .1       0      50     .06       0   130.4    .045       0
   142.4     .06       0
Bank Sta=130.4,142.4
XS Rating Curve= 0 ,0
Exp/Cntr(USF)=0,0
Exp/Cntr=0.3,0.1

Type RM Length L Ch R = 1 ,938     ,96.1,97.8,100.2
XS GIS Cut Line= 2
2143426.44123091631528.6154999712143294.72042392631556.322290407
#Sta/Elev= 25
       0 1326.16    22.8 1322.57    26.8 1321.65      35 1318.92    39.1 1318.38
    43.2 1318.34    47.3 1317.99    55.5 1316.08    59.5 1315.74    67.7 1315.83
    71.8 1315.65    75.9 1315.46      80 1314.97    84.1 1314.28    86.8 1314.07
    88.2 1314.04    92.2 1314.73   93.05 1314.96    99.9 1316.99   110.5 1319.63
   112.7 1320.28   116.8 1321.85   120.9 1323.98     129 1328.92   134.6 1332.77
#Mann= 3 ,-1,0
       0     .06       0      80    .045       0   93.05      .1       0
Bank Sta=80,93.05
XS Rating Curve= 0 ,0
Exp/Cntr(USF)=0,0
Exp/Cntr=0.3,0.1

Type RM Length L Ch R = 1 ,841     ,67.6,67.8,68.3
XS GIS Cut Line= 3
2143431.79555499631480.0894891052143381.32781285631450.818198662
2143280.39232857631455.360295455
#Sta/Elev= 30
       0 1321.31     4.2 1320.05     8.8 1319.14    13.6 1318.53    22.7 1317.78
    25.3 1317.49      37 1316.01    45.8 1314.65    50.4 1314.59    55.1 1314.89
    59.5 1314.96    63.5 1314.37    67.5  1313.3    75.5 1311.78    79.5 1310.93
    83.5 1309.72    87.5 1309.11    93.61309.806   103.5 1311.09   107.5 1311.22
   111.5  1311.1   115.6 1311.28   127.6 1313.36   135.6 1314.57   139.6 1315.81
   143.6 1318.24   147.6 1321.22   151.6 1324.37   155.6 1327.27   159.4 1329.56
#Mann= 4 ,-1,0
       0     .06       0    83.5    .045       0    93.6     .06       0
   98.34      .1       0
Bank Sta=83.5,93.6
XS Rating Curve= 0 ,0
Exp/Cntr(USF)=0,0
Exp/Cntr=0.3,0.1

Type RM Length L Ch R = 1 ,773     ,64.6,64.4,64.2
XS GIS Cut Line= 2
2143448.89937616631380.9973542052143280.38758515631388.718918752
#Sta/Elev= 30
       0 1323.38     4.7 1321.75    16.7 1317.17    20.7 1315.82    24.8 1314.88
    28.8 1314.32    36.8 1313.57    44.8 1313.06    48.8 1312.94    56.8  1312.9
    72.8 1313.53    76.8 1313.33    80.8 1312.43    84.8 1310.75    92.8 1306.28
    96.8 1305.75   100.8 1305.62   108.8 1305.27   112.8 1305.44  113.21 1305.63
   120.9 1309.31   124.9 1310.06   132.9 1310.69   136.9 1311.15   148.9 1312.86
   152.9 1313.67   156.9 1315.26   160.9 1317.87   164.9 1320.82   168.7 1323.49
#Mann= 4 ,-1,0
       0      .1       0      10     .06       0   100.8    .045       0
  113.21      .1       0
Bank Sta=100.8,113.21
XS Rating Curve= 0 ,0
Exp/Cntr(USF)=0,0
Exp/Cntr=0.3,0.1

Type RM Length L Ch R = 1 ,708     ,56.5,60.6,66.1
XS GIS Cut Line= 2
2143458.13497297631314.4808700612143270.09216575631325.836112043
#Sta/Elev= 30
       0 1324.97      22 1315.62      26 1314.13      30 1313.05      34 1312.46
      38 1312.18      46 1312.01    53.5 1311.05    58.1 1310.64    70.1 1310.53
    82.1 1309.83    86.1 1309.23    90.1 1308.42   109.31304.187   114.2 1303.57
   117.8 1303.38   122.2 1303.35   125.81304.133   126.2  1304.2   134.2 1307.45
   138.2 1308.06   150.2 1308.17   155.6 1308.41   166.3 1309.73   170.3 1310.85
   174.3 1313.23   178.3 1316.13   182.3 1319.22   186.3 1321.89   188.4 1322.74
#Mann= 3 ,-1,0
       0      .1       0   109.3    .045       0   125.8     .06       0
Bank Sta=109.3,125.8
XS Rating Curve= 0 ,0
Exp/Cntr(USF)=0,0
Exp/Cntr=0.3,0.1

Type RM Length L Ch R = 1 ,648     ,60.1,58.9,57.7
XS GIS Cut Line= 3
2143466.11361965631264.5922301572143387.38394191631272.162391479
2143268.78474787631235.320939715
#Sta/Elev= 30
       0 1327.28       6 1324.97    26.1 1316.24    34.1 1313.15    38.1 1311.92
    42.1 1311.06    50.2 1309.91    58.2 1309.58    66.2 1308.74    78.3 1308.99
    80.8 1308.79    82.5 1308.56    90.8 1306.37    99.2  1303.7   101.5 1303.35
     116 1302.37   120.2 1302.96  121.22 1303.29   124.3 1304.44   128.5 1305.53
   132.7 1305.47   141.1 1304.24   145.3 1303.88   149.5 1303.92   160.7  1305.1
   178.8 1307.54   186.3 1309.24   191.4 1310.89   199.7 1315.21   203.3 1316.87
#Mann= 4 ,-1,0
       0      .1       0   101.5    .045       0  121.22      .1       0
  129.09     .06       0
Bank Sta=101.5,121.22
XS Rating Curve= 0 ,0
Exp/Cntr(USF)=0,0
Exp/Cntr=0.3,0.1

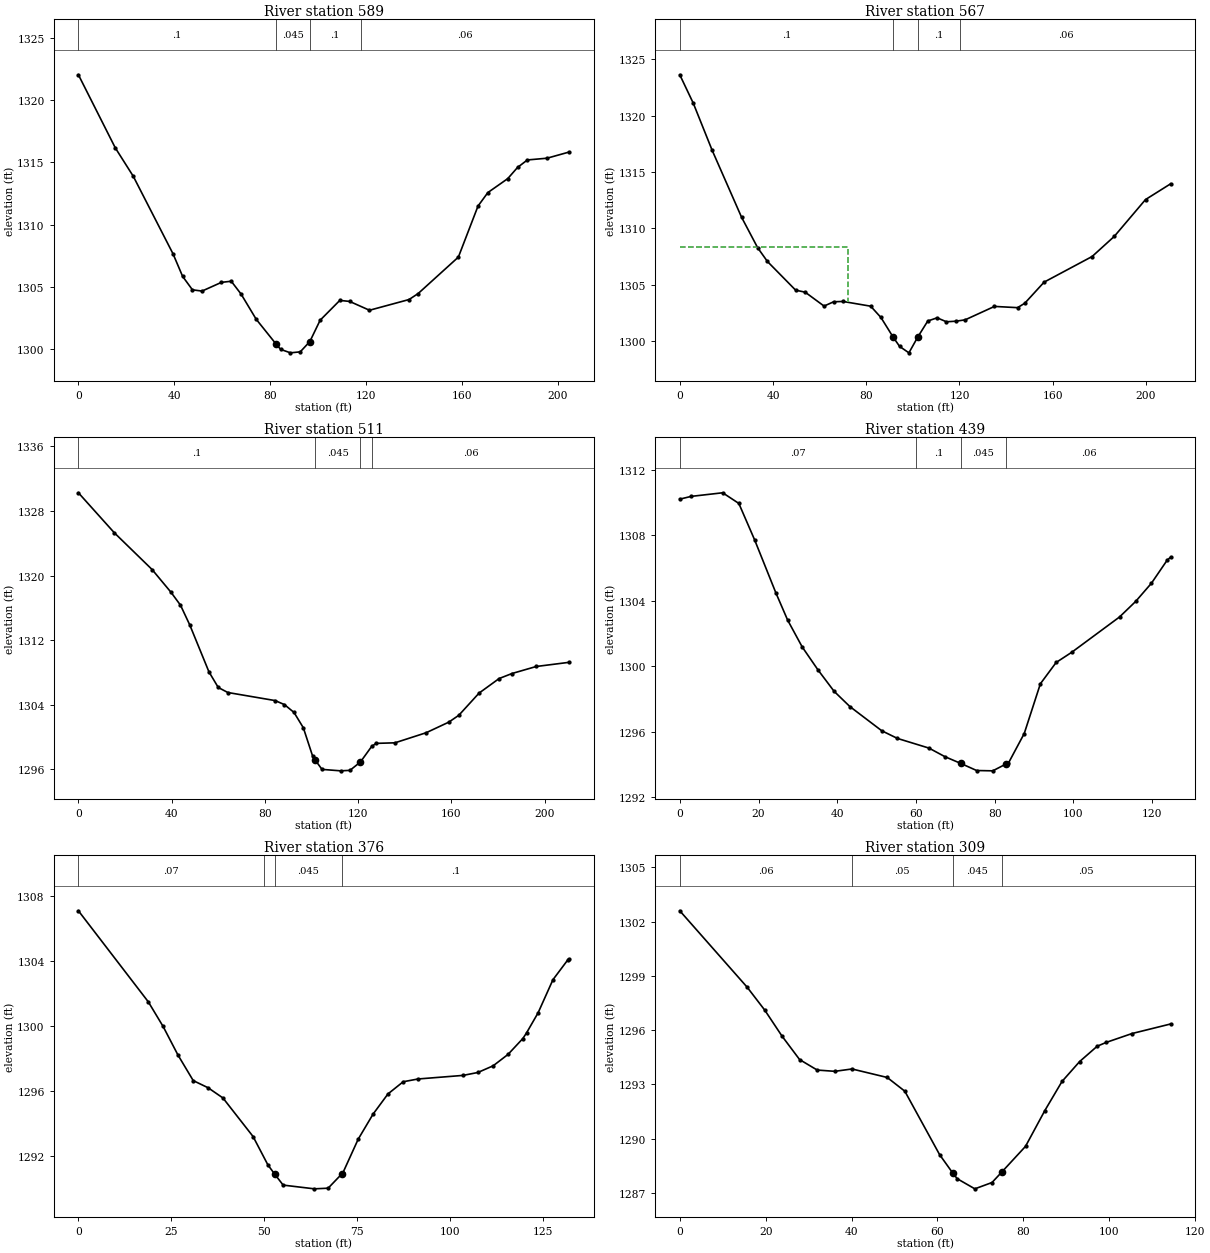
Type RM Length L Ch R = 1 ,589     ,25.6,22.1,19
XS GIS Cut Line= 3
 2143455.5153938631207.5636815362143397.98216776631213.115133172
2143255.15845749631177.787713672
#Sta/Elev= 30
       0 1322.04    15.4 1316.17    22.9 1313.89    39.5 1307.66    43.5 1305.85
    47.6 1304.77    51.6 1304.67    59.7 1305.37    63.8 1305.46    67.9 1304.43
    74.2 1302.41    82.4 1300.44    84.4 1299.99    88.5 1299.71    92.6 1299.79
    96.61300.616   100.9 1302.33   109.1 1303.92   113.2 1303.84   121.5 1303.13
     138 1303.99   141.8 1304.47   158.6  1307.4   166.8  1311.5   170.9 1312.58
   179.2  1313.7   183.3  1314.6   187.4  1315.2   195.6 1315.34   204.9 1315.84
#Mann= 4 ,-1,0
       0      .1       0    82.4    .045       0    96.6      .1       0
   117.8     .06       0
Bank Sta=82.4,96.6
XS Rating Curve= 0 ,0
Exp/Cntr(USF)=0,0
Exp/Cntr=0.3,0.1

Type RM Length L Ch R = 1 ,567     ,55,56,56.6
XS GIS Cut Line= 4
2143461.18827137631167.5188049432143372.16317423631182.961934038
2143336.73481925631184.3245630762143258.15654473631152.529885527
#Sta/Elev= 30
       0 1323.61     5.8 1321.09    13.9 1316.92    26.5    1311    33.4  1308.3
    37.6 1307.08    49.7 1304.54    53.8 1304.36    61.9 1303.13      66 1303.51
      70 1303.54    81.9 1303.12    86.3 1302.12   91.51 1300.39    94.3 1299.56
    98.3 1298.99   102.1 1300.39   106.4 1301.81   110.4 1302.09   114.4 1301.74
   118.4 1301.79   122.4 1301.91     135  1303.1   144.9 1302.99     148 1303.38
   156.3 1305.25   176.9 1307.52   186.4  1309.3   199.8 1312.56   210.6 1313.96
#Mann= 4 ,-1,0
       0      .1       0   91.51    .045       0   102.1      .1       0
  120.35     .06       0
#XS Ineff= 2 , 0
           72.11 1308.35
Permanent Ineff=
       F       F
Bank Sta=91.51,102.1
XS Rating Curve= 0 ,0
Exp/Cntr(USF)=0,0
Exp/Cntr=0.3,0.1

Type RM Length L Ch R = 1 ,511     ,73.8,71.9,69.7
XS GIS Cut Line= 4
2143467.32010204631112.105224071 2143378.2950049631127.548353166
2143342.86664992631128.9109822042143264.28837541631097.116304654
#Sta/Elev= 30
       0 1330.26    15.4 1325.31    31.6 1320.76    39.7 1317.95    43.8 1316.34
    47.8 1313.88      56 1308.09      60 1306.15    64.1 1305.53    84.4 1304.53
    88.4 1304.03    92.5 1303.06    96.5 1301.16   100.5 1297.64   101.7 1297.12
   104.5 1296.01   112.5 1295.83   116.5 1295.89     121 1296.93   125.8 1298.85
   127.7 1299.23   135.8  1299.3   149.2 1300.55   158.9 1301.86   163.2 1302.71
   171.9 1305.46   180.5 1307.26     186 1307.88   196.4 1308.75   210.6 1309.27
#Mann= 4 ,-1,0
       0      .1       0   101.7    .045       0     121      .1       0
  125.81     .06       0
Bank Sta=101.7,121
XS Rating Curve= 0 ,0
Exp/Cntr(USF)=0,0
Exp/Cntr=0.3,0.1

Type RM Length L Ch R = 1 ,439     ,64.1,63.2,63
XS GIS Cut Line= 2
2143403.02894197631054.1417454242143279.26435625631069.653989909
#Sta/Elev= 29
       0  1310.2     2.9 1310.37    10.9 1310.59      15 1309.94      19 1307.72
    24.4 1304.48    27.4 1302.81    31.1 1301.17    35.1 1299.77    39.2 1298.46
    43.2 1297.53    51.3 1296.05    55.3 1295.58    63.3 1294.99    67.4 1294.46
71.396111294.052    75.4 1293.62    79.5  1293.682.89605 1294.02    83.5 1294.08
    87.5 1295.88    91.6 1298.92    95.6 1300.22    99.6 1300.85   111.7    1303
   115.8 1303.95   119.8 1305.06   123.8 1306.47   124.7 1306.66
#Mann= 4 ,-1,0
       0     .07       0      60      .1       071.39611    .045       0
82.89605     .06       0
Bank Sta=71.39611,82.89605
XS Rating Curve= 0 ,0
Exp/Cntr(USF)=0,0
Exp/Cntr=0.3,0.1

Type RM Length L Ch R = 1 ,376     ,68.9,67.3,66.6
XS GIS Cut Line= 2
 2143386.7889084  630992.56209632143255.85382752 631009.73007962
#Sta/Elev= 30
       0 1307.11    18.8 1301.51    22.8 1299.99    26.8 1298.23    30.9 1296.66
    34.9 1296.22    38.9 1295.59      47 1293.22      51 1291.4752.805161290.909
    55.1 1290.23    63.5    1290    67.2 1290.0470.945161290.932    71.2    1291
    75.3 1293.06    79.3  1294.6    83.3 1295.84    87.4 1296.59    91.4 1296.76
   103.5 1296.98   107.5 1297.16   111.6 1297.57   115.6 1298.27   119.6 1299.25
   120.6  1299.6   123.7 1300.83   127.7 1302.87   131.7 1304.09   132.1 1304.14
#Mann= 4 ,-1,0
       0     .07       0      50      .1       052.80516    .045       0
70.94516      .1       0
Bank Sta=52.80516,70.94516
XS Rating Curve= 0 ,0
Exp/Cntr(USF)=0,0
Exp/Cntr=0.3,0.1

Type RM Length L Ch R = 1 ,309     ,80.1,81.2,81.3
XS GIS Cut Line= 2
2143375.56974683630922.2455781312143263.37995605630944.047642737
#Sta/Elev= 24
       0  1302.6    15.7 1298.37    19.8  1297.1    23.8 1295.67    27.9 1294.37
      32 1293.79    36.1 1293.72    40.1 1293.85    48.3 1293.38    52.4 1292.62
    60.5 1289.11    63.6 1288.08    64.6 1287.78    68.7 1287.22    72.7 1287.57
      751288.155    80.5 1289.57      85 1291.55      89 1293.16    93.1 1294.26
    97.2 1295.11    99.3 1295.32   105.3 1295.81   114.3 1296.34
#Mann= 4 ,-1,0
       0     .06       0      40     .05       0    63.6    .045       0
      75     .05       0
Bank Sta=63.6,75
XS Rating Curve= 0 ,0
Exp/Cntr(USF)=0,0
Exp/Cntr=0.3,0.1

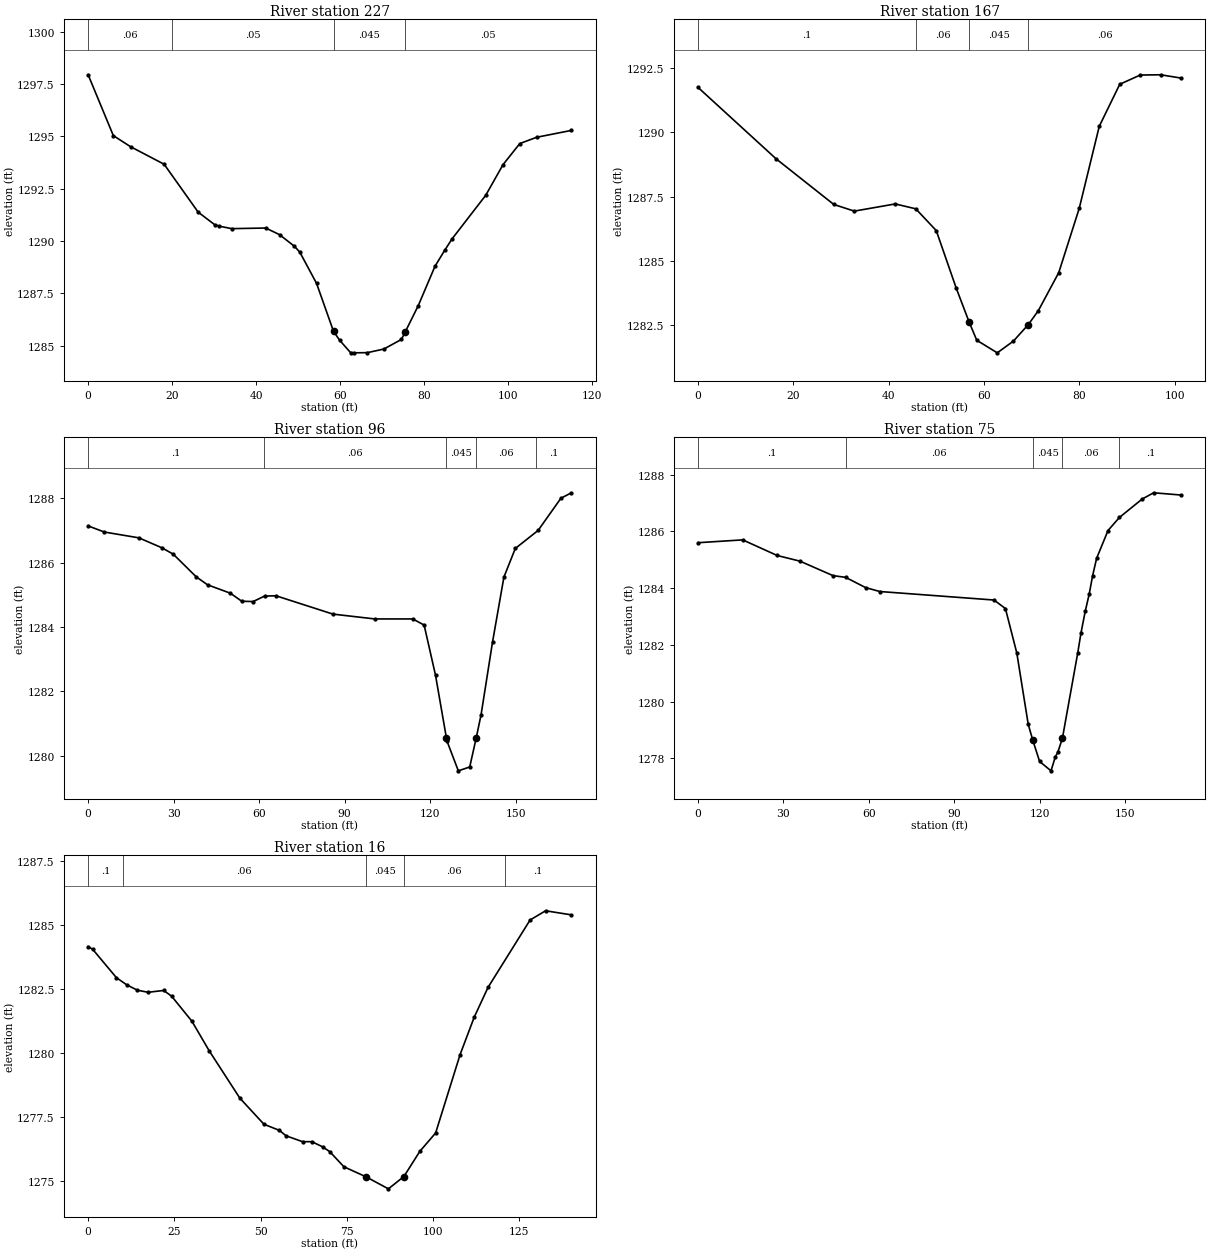
Type RM Length L Ch R = 1 ,227     ,63.4,60.7,58
XS GIS Cut Line= 2
2143362.15007083630848.2333574842143247.92653668630862.705647252
#Sta/Elev= 30
       0 1297.95       6 1295.04    10.1 1294.51    18.1 1293.67    26.2 1291.38
    30.2 1290.77    31.2 1290.71    34.2 1290.59    42.3 1290.62    45.6  1290.3
    49.1 1289.75    50.4 1289.47    54.4 1287.9758.431931285.681    59.9 1285.25
    62.5 1284.66    63.4 1284.65    66.5 1284.66    70.4 1284.83    74.6 1285.29
75.501821285.645    78.6  1286.9    82.6 1288.79    84.9 1289.55    86.7 1290.11
    94.7 1292.19    98.8 1293.65   102.8 1294.66   106.8 1294.96   115.1 1295.29
#Mann= 4 ,-1,0
       0     .06       0      20     .05       058.43193    .045       0
75.50182     .05       0
Bank Sta=58.43193,75.50182
XS Rating Curve= 0 ,0
Exp/Cntr(USF)=0,0
Exp/Cntr=0.3,0.1

Type RM Length L Ch R = 1 ,167     ,66,70.7,75
XS GIS Cut Line= 3
2143348.52378046 630786.662712072143320.93221044630784.179708724
2143252.12670511630810.718975066
#Sta/Elev= 21
       0 1291.76    16.4 1288.97    28.5 1287.19    32.8 1286.93    41.4 1287.21
    45.7 1287.02      50 1286.17    54.2 1283.92    56.9  1282.6    58.5 1281.89
    62.8  1281.4    66.2 1281.86    69.3  1282.5    71.4 1283.04    75.7 1284.53
      80 1287.04    84.2 1290.24    88.5 1291.88    92.8 1292.24    97.1 1292.25
   101.4 1292.12
#Mann= 4 ,-1,0
       0      .1       0    45.7     .06       0    56.9    .045       0
    69.3     .06       0
Bank Sta=56.9,69.3
XS Rating Curve= 0 ,0
Exp/Cntr(USF)=0,0
Exp/Cntr=0.3,0.1

Type RM Length L Ch R = 1 ,96      ,21.1,20.9,20.8
XS GIS Cut Line= 4
2143397.82661694630726.0973710952143376.30279369 630729.06444018
2143321.00594471630732.0445098862143228.56025662630731.150389605
#Sta/Elev= 29
       0 1287.14     5.7 1286.95    17.8 1286.77    25.9 1286.46    29.9 1286.26
    37.9 1285.56    41.9 1285.31    49.9 1285.05    53.9  1284.8    57.9 1284.79
    61.9 1284.96    65.9 1284.97    85.9  1284.4   100.6 1284.25   113.9 1284.25
   117.9 1284.06   121.9  1282.5   125.71280.562   125.9 1280.46   129.9 1279.53
   133.9 1279.65   136.2 1280.56   137.9 1281.28   141.9 1283.53   145.9 1285.55
   149.9 1286.44   157.9    1287   165.9    1288   169.6 1288.17
#Mann= 5 ,-1,0
       0      .1       0   61.73     .06       0   125.7    .045       0
   136.2     .06       0   157.1      .1       0
Bank Sta=125.7,136.2
XS Rating Curve= 0 ,0
Exp/Cntr(USF)=0,0
Exp/Cntr=0.3,0.1

Type RM Length L Ch R = 1 ,75      ,58.9,58.9,58.9
XS GIS Cut Line= 4
2143387.75870663630705.2303828442143366.23488338630708.197451929
 2143310.9380344630711.1775216352143218.49234632630710.283401355
#Sta/Elev= 29
       0  1285.6    15.7  1285.7    27.8 1285.15    35.8 1284.95    47.4 1284.44
    51.8 1284.38    58.8 1284.02    63.8 1283.88   103.9 1283.58   107.9 1283.28
   111.9 1281.71   115.9  1279.2   117.5 1278.64   119.9 1277.89   123.9 1277.56
   125.4 1278.05   126.3 1278.22   127.9 1278.71   133.3 1281.73   134.4 1282.41
   135.9 1283.18   137.3 1283.79   138.5 1284.44   139.9 1285.05   143.9 1286.03
   147.9 1286.49   155.9 1287.14   159.9 1287.36   169.6 1287.28
#Mann= 5 ,-1,0
       0      .1       0    51.8     .06       0   117.5    .045       0
   127.9     .06       0   147.9      .1       0
Bank Sta=117.5,127.9
XS Rating Curve= 0 ,0
Exp/Cntr(USF)=0,0
Exp/Cntr=0.3,0.1

Type RM Length L Ch R = 1 ,16      ,,,
XS GIS Cut Line= 5
2143350.46791441630689.6658461632143326.69543688630679.649922837
 2143305.2706466630664.6243912842143259.22922261630648.239420229
 2143220.2728602630653.670505609
#Sta/Elev= 30
       0 1284.15     1.3 1284.05     8.2 1282.94    11.2 1282.66    14.3 1282.45
    17.4 1282.37    21.9 1282.44    24.2 1282.22    30.1 1281.24    35.1 1280.09
      44 1278.24      51 1277.22    55.5 1276.98    57.4 1276.77    62.2 1276.54
    64.9 1276.54      68 1276.34    70.1 1276.15    74.2 1275.56    80.6 1275.17
    87.1  1274.791.598491275.181    96.2 1276.16   100.8 1276.88   107.9 1279.94
     112  1281.4     116 1282.56   128.2 1285.19   132.7 1285.55   140.2 1285.39
#Mann= 5 ,-1,0
       0      .1       0      10     .06       0    80.6    .045       0
91.59849     .06       0  120.83      .1       0
Bank Sta=80.6,91.59849
XS Rating Curve= 0 ,0
Exp/Cntr(USF)=0,0
Exp/Cntr=0.3,0.1
LCMann Table=0

Chan Stop Cuts=-1
Use User Specified Reach Order=0
Composite Channel Slope=5